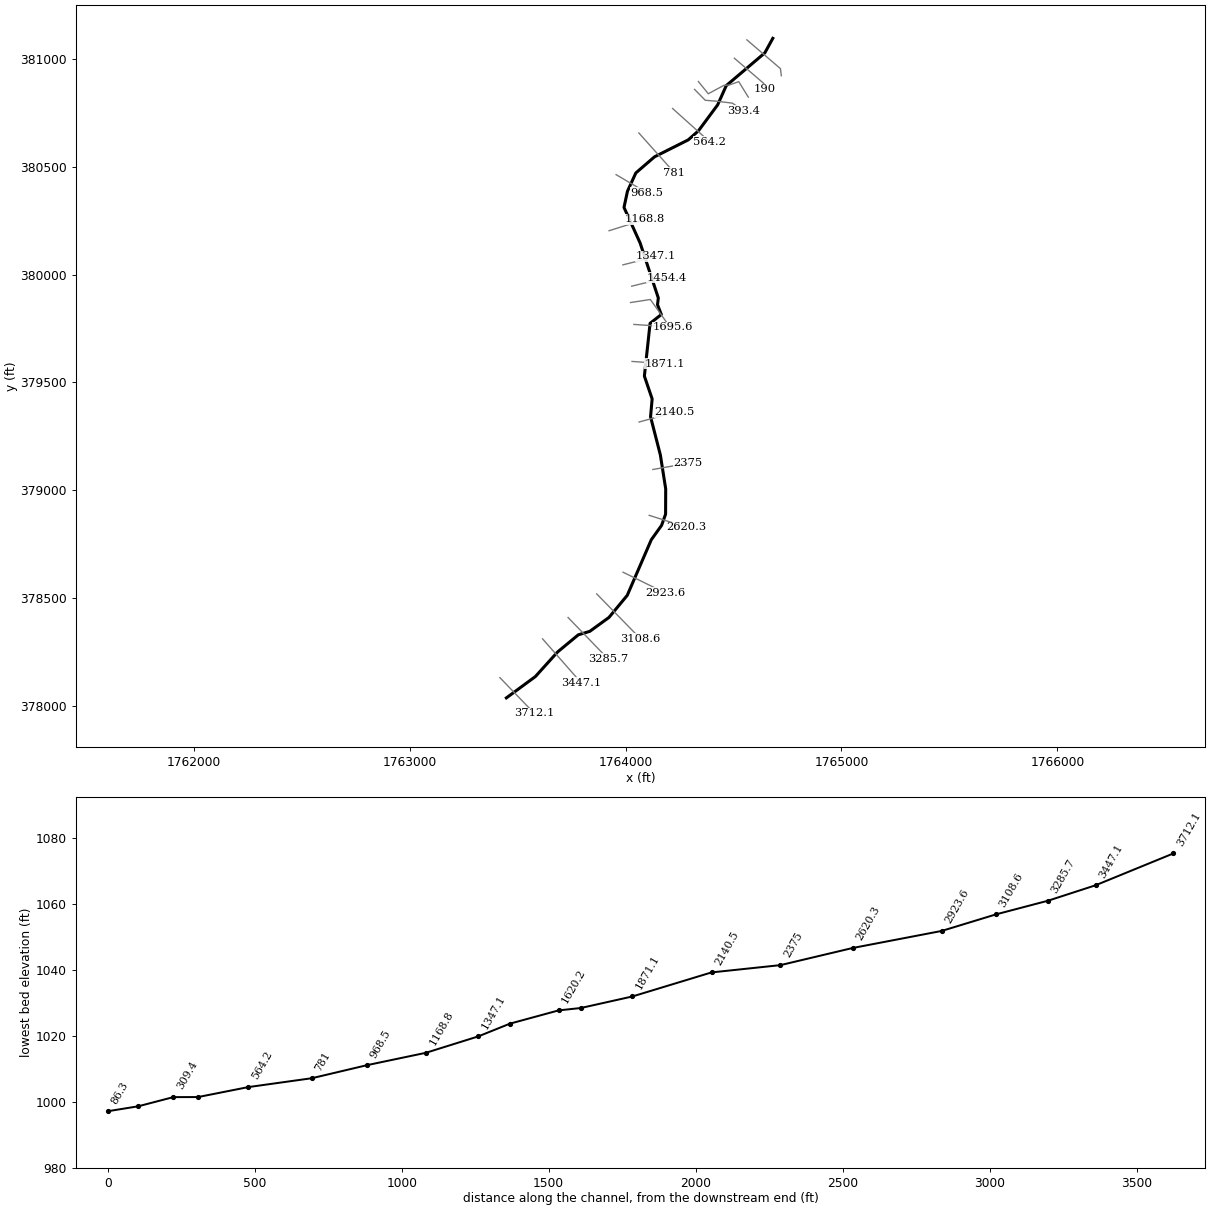
--- LTLAURCK.prj (project) ---

Proj Title=LTLAURCK
Current Plan=p01
Default Exp/Contr=0,0
English Units
Geom File=g01
Flow File=f01
Plan File=p01
BEGIN DESCRIPTION:
END DESCRIPTION:
DSS Export Rating Curves= 0
DSS Export Rating Curve Sorted= 0
DSS Export Volume Flow Curves= 0
DXF OffsetX= 0
DXF OffsetY= 0
DXF ScaleX= 0
DXF ScaleY= 0

--- LTLAURCK.p01 (plan) ---

Plan Title=Floodplain
Program Version=4.00
Geom File=g01
Flow File=f01
K Sum by GR=0
Std Step Tol=0.01
Critical Tol=0.01
Num of Std Step Trials=20
Max Error Tol=0.3
Flow Tol Ratio=0.001
Split Flow NTrial=30
Split Flow Tol=0.02
Split Flow Ratio=0.02
Log Output Level=0
Friction Slope Method=1
Unsteady Friction Slope Method=2
Unsteady Bridges Friction Slope Method=1
Global Log Level=0
CheckData=False
Run HTab=0
Run UNet=0
Run PostProcess=0
UNET Theta=0
UNET Theta Warmup=0
UNET ZTol=0
UNET ZSATol=0
UNET MxIter=0
UNET MaxInSteps=0
UNET DtIC=0
UNET DtMin=0
UNET MaxCRTS=0
UNET WFStab=0
UNET SFStab=0
UNET WFX=0
UNET SFX=0
UNET DSS MLevel=0
UNET DZMax Abort=0
UNET Convert EG Bridges=0
UNET Use Existing IB Tables=0
UNET Froude Limit=0
UNET Froude Power=0
Write IC File=0
Echo Input=False
Echo Output=False
Write Detailed=0

--- LTLAURCK.f01 (steady flow) ---

Flow Title=NFF Regression Equation
Program Version=4.10
Number of Profiles= 1
Profile Names=P100yr
River Rch & RM=LTLAURCK,Main            ,3712.1
 896.013
River Rch & RM=LTLAURCK,Main            ,564.2
979.5455
River Rch & RM=LTLAURCK,Main            ,86.3
982.9248
Boundary for River Rch & Prof#=LTLAURCK,Main            , 1
Up Type= 0
Dn Type= 3
Dn Slope=0.010241
DSS Import GetInterval= 0
DSS Import GetPeak= 0
DSS Import FillOption= 0

--- LTLAURCK.g01 (geometry) ---

Geom Title=USGS 10m DEM
Program Version=4.10

River Reach=LTLAURCK        ,Main
Reach XY= 30
     1763447.547      378035.498     1763581.791      378134.402
     1763684.835      378248.679     1763780.664      378328.207
      1763834.22      378344.525      1763922.93      378409.041
     1764007.534      378511.534     1764118.971      378769.598
     1764166.727       378836.55     1764185.236      378888.477
      1764185.75      379005.697     1764161.053      379163.294
     1764115.598      379340.787      1764122.93      379423.631
     1764087.006       379529.57     1764113.399      379774.438
     1764165.452      379815.347     1764147.856      379860.801
     1764151.522      379892.327     1764067.211      380147.605
     1763992.526      380312.522      1764008.56      380387.635
     1764047.416      380472.678     1764133.927      380547.459
     1764290.378      380626.271     1764337.299       380668.06
     1764426.307      380788.491     1764466.315      380878.005
     1764644.901       381029.96     1764681.994      381097.597

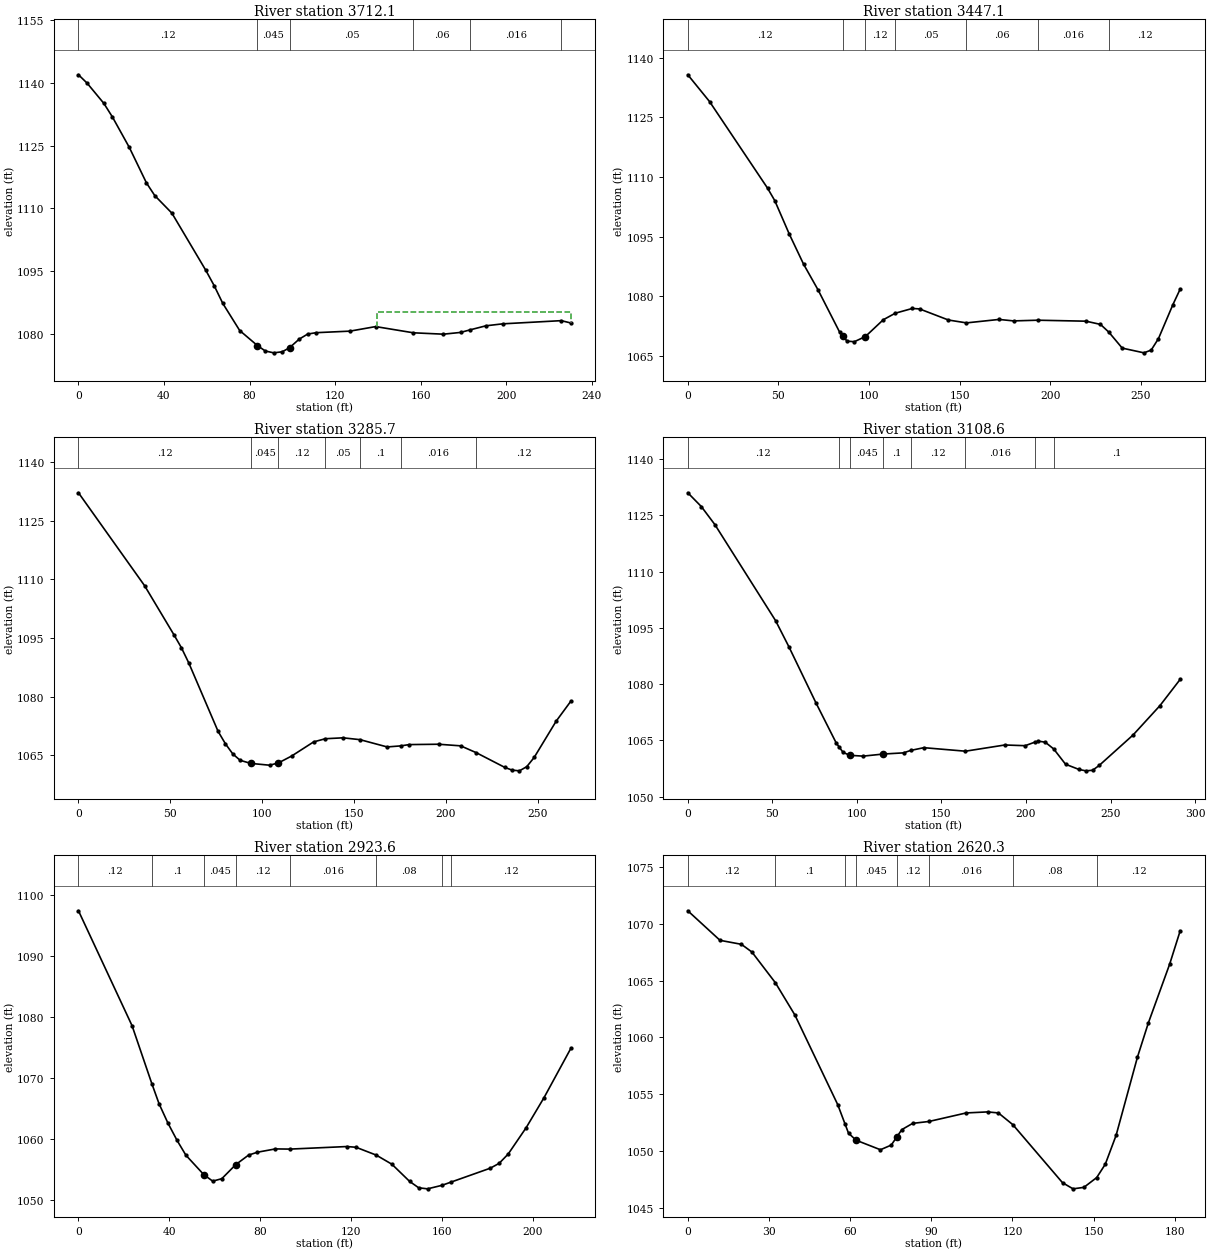
Type RM Length L Ch R = 1 ,3712.1  ,266,265,263.9
XS GIS Cut Line= 2
      1763417.51      378129.594      1763577.15      377963.632
#Sta/Elev= 30
       0 1141.99       4 1140.01    11.9 1135.12    15.9 1131.86    23.8 1124.57
    31.8 1116.08    35.7 1113.04    43.7 1108.84    59.6 1095.11    63.5 1091.44
    67.5 1087.22    75.4 1080.73    83.7 1077.12    87.4 1075.82    91.3 1075.38
    95.3 1075.63    98.7  1076.6   103.2 1078.65   107.2 1079.88   111.2 1080.21
     127 1080.58     139 1081.67  156.65 1080.18   170.7 1079.85   178.7 1080.27
  183.191080.889   190.6 1081.86   198.5 1082.33   225.81083.091   230.3 1082.53
#Mann= 6 ,-1 , 0
       0     .12       0    83.7    .045       0    98.7     .05       0
  156.65     .06       0  183.19    .016       0   225.8     .12       0
#XS Ineff= 2 , 0
                          139.49         1085.14
Permanent Ineff=
       F       F
Bank Sta=83.7,98.7
XS Rating Curve= 0 ,0
Exp/Cntr=0.3,0.1

Type RM Length L Ch R = 1 ,3447.1  ,159.4,161.4,163.2
XS GIS Cut Line= 2
     1763615.366      378309.563     1763794.547      378105.248
#Sta/Elev= 30
       0 1135.72      12 1128.98      44 1107.19      48 1104.04      56 1095.63
    63.9 1088.04    71.9 1081.56    83.9 1070.84    85.4 1070.02    87.9 1068.66
    91.9 1068.51   98.02 1069.81   107.9 1074.04  114.541075.689   123.9 1076.88
   127.9 1076.77   143.9 1073.97  153.831073.252   171.8 1074.12   179.8 1073.75
  193.111073.926   219.8 1073.68   227.8 1072.87   232.41070.925   239.8  1066.9
   251.8 1065.71   255.8 1066.41   259.8 1069.29   267.8 1077.88   271.8 1081.77
#Mann= 7 ,-1 , 0
       0     .12       0    85.4    .045       0   98.02     .12       0
  114.54     .05       0  153.83     .06       0  193.11    .016       0
   232.4     .12       0
Bank Sta=85.4,98.02
XS Rating Curve= 0 ,0
Exp/Cntr=0.3,0.1

Type RM Length L Ch R = 1 ,3285.7  ,177.8,177.1,176.3
XS GIS Cut Line= 2
     1763733.429      378408.723     1763919.547      378215.925
#Sta/Elev= 30
       0 1132.12      36 1108.36      52 1095.79      56 1092.53      60 1088.66
      76 1071.12      80 1067.94      84 1065.36      88 1063.73    93.8 1062.94
     104 1062.48   108.8 1063.06     116 1064.82     128 1068.44  134.37 1069.25
     144 1069.48  153.261069.008     168 1067.15  175.421067.418     180 1067.75
     196 1067.84     208 1067.43  216.481065.685     232 1061.93     236 1061.22
     240 1061.04     244 1062.11     248 1064.45     260 1073.74     268 1078.85
#Mann= 7 ,-1 , 0
       0     .12       0    93.8    .045       0   108.8     .12       0
  134.37     .05       0  153.26      .1       0  175.42    .016       0
  216.48     .12       0
Bank Sta=93.8,108.8
XS Rating Curve= 0 ,0
Exp/Cntr=0.3,0.1

Type RM Length L Ch R = 1 ,3108.6  ,177.3,185,192.7
XS GIS Cut Line= 2
     1763866.114      378518.296     1764069.287      378309.675
#Sta/Elev= 30
       0 1130.98       8 1127.31      16 1122.51    51.9 1096.92    59.8 1089.94
    75.8 1074.99    87.8 1064.29    89.41063.306    91.8 1061.83    95.7 1061.03
   103.7 1060.81   115.7 1061.37   127.6 1061.68  131.73 1062.32   139.6 1063.06
  164.211062.124   187.5 1063.78   199.5 1063.59  205.441064.565   207.4  1064.8
   211.4 1064.52  216.39 1062.72   223.4 1058.65   231.4 1057.25   235.4 1056.89
   239.4 1057.04   243.3 1058.33   263.3 1066.43   279.2 1074.25   291.2 1081.27
#Mann= 8 ,-1 , 0
       0     .12       0    89.4      .1       0    95.7    .045       0
   115.7      .1       0  131.73     .12       0  164.21    .016       0
  205.44     .12       0  216.39      .1       0
Bank Sta=95.7,115.7
XS Rating Curve= 0 ,0
Exp/Cntr=0.3,0.1

Type RM Length L Ch R = 1 ,2923.6  ,299.9,303.3,306.5
XS GIS Cut Line= 2
     1763988.131      378619.058     1764182.568      378523.216
#Sta/Elev= 30
       0 1097.41    23.6 1078.58   32.291069.102    35.5 1065.78    39.4 1062.62
    43.4  1059.8    47.3 1057.37    55.2 1054.18    59.1 1053.12    63.1 1053.52
   69.25 1055.83    74.9 1057.39    78.8 1057.86    86.7  1058.4   93.171058.371
   118.2 1058.79   122.2 1058.67  131.081057.391     138 1055.89   145.8 1053.08
   149.8 1052.03   153.7 1051.86  159.98 1052.43  164.01 1052.96   181.3 1055.24
   185.2 1056.03   189.2 1057.56   197.1 1061.87     205 1066.81   216.8 1074.88
#Mann= 8 ,-1 , 0
       0     .12       0   32.29      .1       0    55.2    .045       0
   69.25     .12       0   93.17    .016       0  131.08     .08       0
  159.98     .06       0  164.01     .12       0
Bank Sta=55.2,69.25
XS Rating Curve= 0 ,0
Exp/Cntr=0.3,0.1

Type RM Length L Ch R = 1 ,2620.3  ,233.9,245.3,255.7
XS GIS Cut Line= 2
     1764109.354      378883.021     1764282.828      378827.904
#Sta/Elev= 30
       0 1071.15    11.9 1068.55    19.8  1068.2    23.7 1067.52   32.361064.821
    39.6 1061.97    55.4  1054.1   58.161052.361    59.4 1051.58    62.2 1050.96
    71.2 1050.12    75.2 1050.53    77.2 1051.23    79.1 1051.89    83.1 1052.44
   89.151052.609   102.9 1053.36   110.8 1053.45   114.8 1053.36  120.141052.328
   138.5 1047.22   142.4 1046.68   146.4 1046.81  151.13 1047.67   154.3 1048.84
   158.3 1051.38   166.2 1058.27   170.2 1061.26   178.1 1066.45     182 1069.39
#Mann= 8 ,-1 , 0
       0     .12       0   32.36      .1       0   58.16     .12       0
    62.2    .045       0    77.2     .12       0   89.15    .016       0
  120.14     .08       0  151.13     .12       0
Bank Sta=62.2,77.2
XS Rating Curve= 0 ,0
Exp/Cntr=0.3,0.1

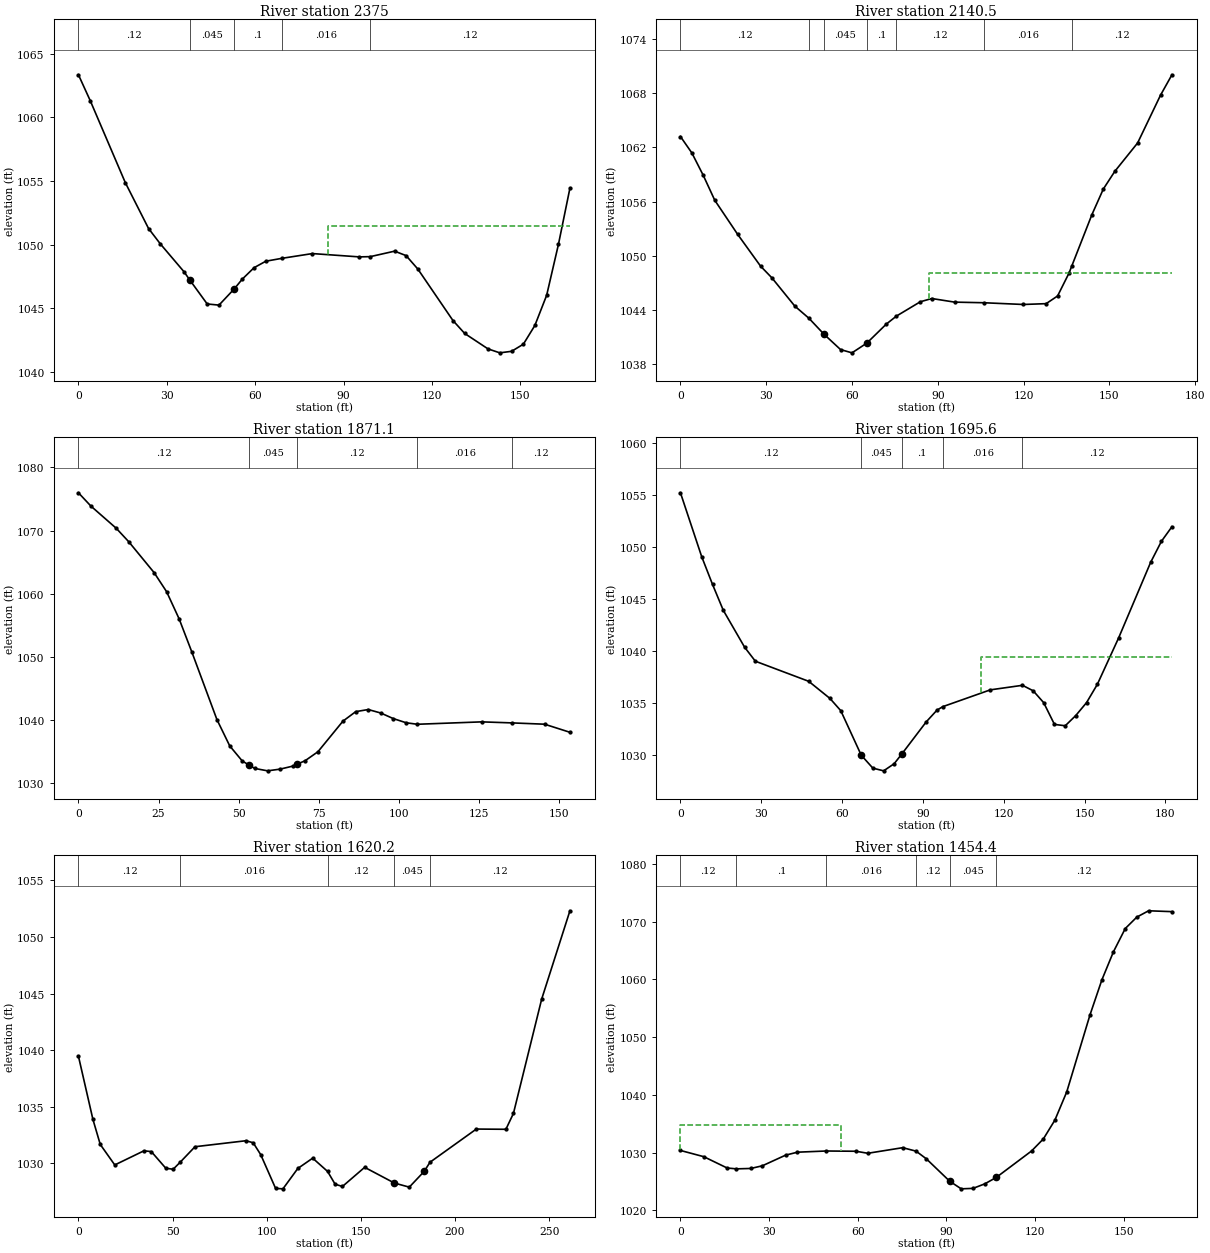
Type RM Length L Ch R = 1 ,2375    ,232.1,234.4,236.4
XS GIS Cut Line= 2
     1764126.305      379095.963     1764290.641      379124.779
#Sta/Elev= 30
       0 1063.34       4 1061.31    15.9 1054.87    23.8 1051.26    27.8 1050.05
    35.8 1047.87    37.9 1047.18    43.7 1045.33    47.7 1045.24    52.9 1046.52
    55.6 1047.28    59.6 1048.18    63.6 1048.69   69.061048.917    79.4 1049.29
    95.3 1049.03   99.041049.049   107.3 1049.48   111.2 1049.13   115.2 1048.07
   127.1 1044.03   131.1 1043.01     139  1041.8     143 1041.49     147 1041.61
     151 1042.17   154.9 1043.64   158.9 1046.01   162.9 1050.01   166.8 1054.43
#Mann= 5 ,-1 , 0
       0     .12       0    37.9    .045       0    52.9      .1       0
   69.06    .016       0   99.04     .12       0
#XS Ineff= 2 , 0
                           84.56         1051.46
Permanent Ineff=
       F       F
Bank Sta=37.9,52.9
XS Rating Curve= 0 ,0
Exp/Cntr=0.3,0.1

Type RM Length L Ch R = 1 ,2140.5  ,277.3,269.4,261.5
XS GIS Cut Line= 2
     1764062.386      379316.298     1764228.141      379361.758
#Sta/Elev= 30
       0 1063.21       4 1061.39       8  1058.9      12 1056.16      20 1052.39
      28 1048.88      32 1047.57      40 1044.45   44.941043.104    50.2 1041.34
      56 1039.64      60 1039.28    65.2 1040.36      72 1042.46   75.56 1043.35
    83.9 1044.93    87.9 1045.29    95.9 1044.89  106.191044.821   119.9 1044.63
   127.9 1044.72   131.9 1045.57   135.9  1048.1  136.821048.843   143.9 1054.56
   147.9  1057.4   151.9 1059.35   159.9  1062.5   167.9 1067.78   171.9 1070.04
#Mann= 7 ,-1 , 0
       0     .12       0   44.94      .1       0    50.2    .045       0
    65.2      .1       0   75.56     .12       0  106.19    .016       0
  136.82     .12       0
#XS Ineff= 2 , 0
                              87         1048.14
Permanent Ineff=
       F       F
Bank Sta=50.2,65.2
XS Rating Curve= 0 ,0
Exp/Cntr=0.3,0.1

Type RM Length L Ch R = 1 ,1871.1  ,175.8,175.5,175.2
XS GIS Cut Line= 2
     1764029.833      379597.548      1764182.75      379587.062
#Sta/Elev= 30
       0 1075.98     3.9 1073.87    11.8 1070.36    15.7 1068.23    23.6 1063.35
    27.5 1060.33    31.4 1056.04    35.4 1050.75    43.2 1040.09    47.2 1035.92
    51.1 1033.54    53.2  1032.9      55 1032.36      59 1031.98    62.9 1032.25
    66.8 1032.72    68.2 1033.03    70.7 1033.58    74.7    1035    82.5 1039.84
    86.5 1041.35    90.4 1041.68    94.3 1041.13    98.2 1040.25   102.2 1039.59
  105.681039.349   125.8 1039.73  135.281039.565   145.4 1039.36   153.3 1038.08
#Mann= 5 ,-1 , 0
       0     .12       0    53.2    .045       0    68.2     .12       0
  105.68    .016       0  135.28     .12       0
Bank Sta=53.2,68.2
XS Rating Curve= 0 ,0
Exp/Cntr=0.3,0.1

Type RM Length L Ch R = 1 ,1695.6  ,133.4,75.3,54.1
XS GIS Cut Line= 2
     1764038.167      379769.423     1764220.163      379756.943
#Sta/Elev= 30
       0 1055.19     7.9 1049.04    11.9 1046.39    15.9  1043.9    23.8 1040.36
    27.8 1039.01    47.6 1037.08    55.5 1035.43    59.5 1034.26    67.1 1029.98
    71.4 1028.74    75.4 1028.48    79.3 1029.16    82.1 1030.08    91.2 1033.18
    95.2 1034.31   97.331034.643     115 1036.26  126.931036.696   130.9 1036.17
   134.8 1035.03   138.8 1032.94   142.8 1032.81   146.7 1033.79   150.7 1035.03
   154.7 1036.78   162.6 1041.24   174.5 1048.51   178.5 1050.53   182.4 1051.93
#Mann= 5 ,-1 , 0
       0     .12       0    67.1    .045       0    82.1      .1       0
   97.33    .016       0  126.93     .12       0
#XS Ineff= 2 , 0
                          111.36         1039.38
Permanent Ineff=
       F       F
Bank Sta=67.1,82.1
XS Rating Curve= 0 ,0
Exp/Cntr=0.3,0.1

Type RM Length L Ch R = 1 ,1620.2  ,96.8,165.9,195.6
XS GIS Cut Line= 4
     1764022.893      379870.986      1764114.64      379885.165
      1764194.61      379772.496     1764222.715      379761.914
#Sta/Elev= 30
       0 1039.48     7.7 1033.89    11.6 1031.68    19.3 1029.87    34.8 1031.12
    38.7 1031.05    46.4 1029.58    50.3 1029.49    54.2 1030.14    61.9 1031.48
      89 1032.01    92.8 1031.83    96.8 1030.78   104.7  1027.8   108.6 1027.76
   116.5 1029.56   124.4 1030.47   132.3  1029.3   136.3 1028.17   140.2 1027.97
     152 1029.66   167.8 1028.27   175.7 1027.91   183.6  1029.3   186.7 1030.11
   211.3 1033.04     227 1033.02     231 1034.42     246 1044.52     261 1052.32
#Mann= 5 ,-1 , 0
       0     .12       0    54.2    .016       0   132.3     .12       0
   167.8    .045       0   186.7     .12       0
Bank Sta=167.8,183.6
XS Rating Curve= 0 ,0
Exp/Cntr=0.3,0.1

Type RM Length L Ch R = 1 ,1454.4  ,107.1,107.2,107.5
XS GIS Cut Line= 2
     1764028.271      379947.027      1764189.88      379986.393
#Sta/Elev= 30
       0 1030.38     7.9  1029.3    15.8 1027.34   18.931027.191    23.8 1027.26
    27.7 1027.72    35.6 1029.57    39.6 1030.08   49.331030.285    59.4 1030.24
    63.4 1029.89    75.2 1030.86   79.731030.257    83.2 1028.93    91.1 1025.05
      95 1023.73      99 1023.81     103  1024.6   106.9 1025.72   118.8 1030.29
   122.8 1032.38   126.7 1035.64   130.7 1040.52   138.6 1053.91   142.6 1059.94
   146.5 1064.79   150.5 1068.82   154.4  1070.8   158.4  1071.9   166.3 1071.75
#Mann= 6 ,-1 , 0
       0     .12       0   18.93      .1       0   49.33    .016       0
   79.73     .12       0    91.1    .045       0   106.9     .12       0
#XS Ineff= 2 , 0
           54.23 1034.71
Permanent Ineff=
       F       F
Bank Sta=91.1,106.9
XS Rating Curve= 0 ,0
Exp/Cntr=0.3,0.1

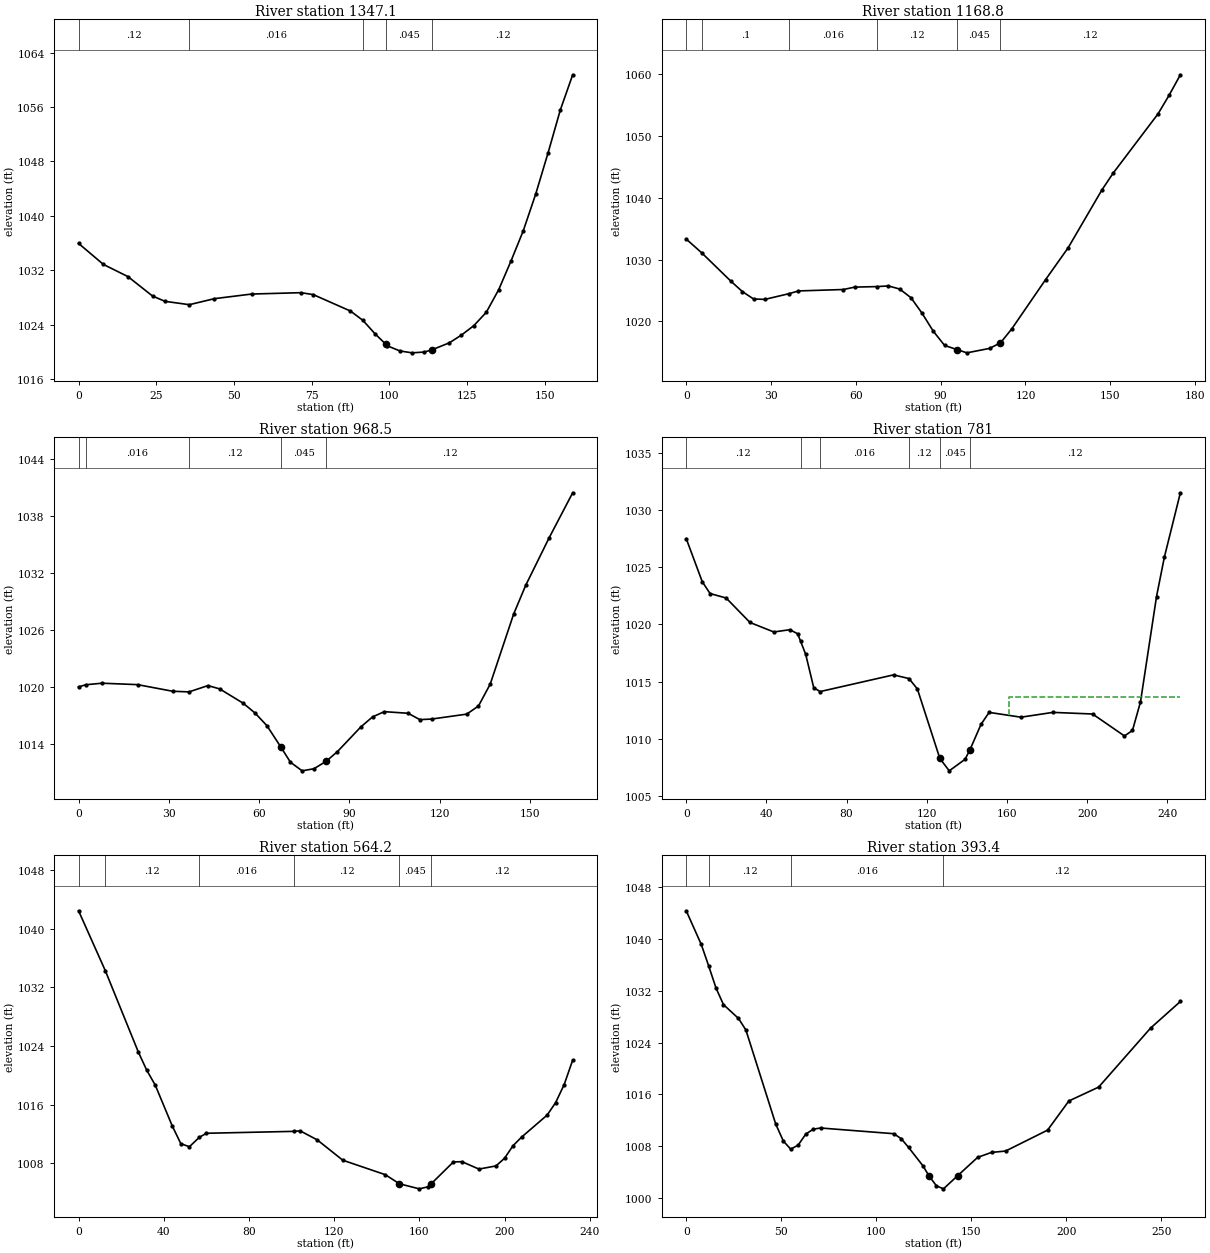
Type RM Length L Ch R = 1 ,1347.1  ,176.9,178.3,179.6
XS GIS Cut Line= 2
       1763987.5      380045.928     1764141.677      380084.867
#Sta/Elev= 30
       0 1035.96       8 1032.87    15.9 1031.08    23.8 1028.23    27.8 1027.45
   35.641026.956    43.7 1027.84    55.7 1028.52    71.6 1028.72    75.5 1028.44
    87.5 1026.02   91.491024.655    95.4 1022.68    98.8 1021.17    99.4  1020.9
   103.4 1020.16   107.3 1019.88   111.3    1020   113.8 1020.34   119.3 1021.35
   123.2 1022.49   127.2 1023.88   131.2 1025.84   135.2 1029.17   139.1 1033.32
   143.1 1037.82   147.1 1043.21   151.1  1049.3     155 1055.54     159 1060.74
#Mann= 5 ,-1 , 0
       0     .12       0   35.64    .016       0   91.49     .12       0
    98.8    .045       0   113.8     .12       0
Bank Sta=98.8,113.8
XS Rating Curve= 0 ,0
Exp/Cntr=0.3,0.1

Type RM Length L Ch R = 1 ,1168.8  ,219.4,200.3,180.8
XS GIS Cut Line= 2
     1763923.323      380204.405     1764090.073      380256.879
#Sta/Elev= 30
       0 1033.33    5.461031.109    15.9 1026.46    19.9 1024.81    23.8 1023.63
    27.8 1023.56   36.421024.493    39.7 1024.93    55.6 1025.16    59.6 1025.55
   67.381025.631    71.5 1025.74    75.5 1025.24    79.5 1023.83    83.4 1021.33
    87.4  1018.4    91.4  1016.1    95.9 1015.41    99.3  1014.9   107.3 1015.62
   110.9 1016.46   111.2 1016.53   115.2 1018.81   127.1 1026.75   135.1 1031.92
     147 1041.26     151    1044   166.9 1053.62   170.8 1056.62   174.8 1059.95
#Mann= 6 ,-1 , 0
       0     .12       0    5.46      .1       0   36.42    .016       0
   67.38     .12       0    95.9    .045       0   110.9     .12       0
Bank Sta=95.9,110.9
XS Rating Curve= 0 ,0
Exp/Cntr=0.3,0.1

Type RM Length L Ch R = 1 ,968.5   ,194.5,187.6,180.6
XS GIS Cut Line= 2
     1763955.992      380464.752     1764097.372      380381.268
#Sta/Elev= 30
       0    1020    2.411020.229     7.8 1020.39    19.6 1020.24    31.3 1019.54
   36.711019.475      43 1020.14    46.9 1019.79    54.7 1018.28    58.6 1017.26
    62.6 1015.91    67.3 1013.62    70.4 1012.06    74.3 1011.15    78.2 1011.37
    82.3 1012.16      86 1013.17    93.8 1015.78    97.7 1016.84   101.6 1017.39
   109.5 1017.22   113.4 1016.55   117.3 1016.61     129 1017.13   132.9 1017.99
   136.8  1020.3   144.6  1027.7   148.6 1030.72   156.4 1035.74   164.2 1040.47
#Mann= 5 ,-1 , 0
       0     .06       0    2.41    .016       0   36.71     .12       0
    67.3    .045       0    82.3     .12       0
Bank Sta=67.3,82.3
XS Rating Curve= 0 ,0
Exp/Cntr=0.3,0.1

Type RM Length L Ch R = 1 ,781     ,214.3,216.7,219.1
XS GIS Cut Line= 2
     1764061.294      380658.371     1764225.411      380474.487
#Sta/Elev= 30
       0 1027.49       8 1023.72    11.9 1022.69    19.9  1022.3    31.8 1020.16
    43.7 1019.33    51.7 1019.53    55.6 1019.17   57.011018.535    59.6 1017.37
    63.6 1014.46   66.771014.119   103.4 1015.58  111.121015.257   115.3 1014.35
   126.5 1008.28   131.2 1007.19   139.1  1008.2   141.5 1009.02   147.1 1011.27
   151.1  1012.3     167 1011.88   182.9  1012.3   202.7 1012.16   218.6 1010.24
   222.6 1010.72   226.6 1013.21   234.6 1022.42   238.5 1025.86   246.5  1031.5
#Mann= 6 ,-1 , 0
       0     .12       0   57.01      .1       0   66.77    .016       0
  111.12     .12       0   126.5    .045       0   141.5     .12       0
#XS Ineff= 2 , 0
                          160.83         1013.64
Permanent Ineff=
       F       F
Bank Sta=126.5,141.5
XS Rating Curve= 0 ,0
Exp/Cntr=0.3,0.1

Type RM Length L Ch R = 1 ,564.2   ,156.2,170.8,184.9
XS GIS Cut Line= 2
     1764217.621      380771.914     1764390.046      380616.827
#Sta/Elev= 30
       0 1042.47   12.571034.277      28 1023.21      32 1020.69      36 1018.65
      44 1013.06      48 1010.66      52 1010.24   56.73 1011.54      60 1012.08
   100.9 1012.34     104 1012.41     112 1011.18     124  1008.4   143.9 1006.43
   150.6 1005.18   159.9 1004.49   163.9 1004.76   165.6 1005.21   175.9 1008.16
   179.9  1008.2   187.9 1007.19   195.9 1007.62   199.9 1008.66   203.9 1010.38
   207.9 1011.55   219.9 1014.56   223.9 1016.27   227.9 1018.73   231.9 1022.07
#Mann= 6 ,-1 , 0
       0     .06       0   12.57     .12       0   56.73    .016       0
   100.9     .12       0   150.6    .045       0   165.6     .12       0
Bank Sta=150.6,165.6
XS Rating Curve= 0 ,0
Exp/Cntr=0.3,0.1

Type RM Length L Ch R = 1 ,393.4   ,69.4,84,113.4
XS GIS Cut Line= 6
     1764319.464      380860.613     1764368.943      380810.092
     1764418.943      380805.925     1764454.881      380801.759
     1764494.985       380796.55     1764546.548      380761.134
#Sta/Elev= 30
       0 1044.29     7.9 1039.11    11.8 1035.81    15.7 1032.37    19.6 1029.84
    27.5 1027.71    31.4 1025.93    47.1 1011.45    51.1 1008.83      55 1007.58
    58.9  1008.2    62.9 1009.89    66.8 1010.65    70.7 1010.84   109.3 1009.96
   113.2 1009.18     117 1007.86   124.5 1005.05   127.9 1003.42   131.7 1001.93
   135.4 1001.47   142.9  1003.5   153.4 1006.32   160.7 1007.08   168.1 1007.29
   190.2 1010.51   201.4    1015   217.1 1017.14   244.4 1026.22   260.1 1030.32
#Mann= 4 ,-1 , 0
       0     .06       0    11.8     .12       0      55    .016       0
   135.4     .12       0
Bank Sta=127.9,142.9
XS Rating Curve= 0 ,0
Exp/Cntr=0.3,0.1

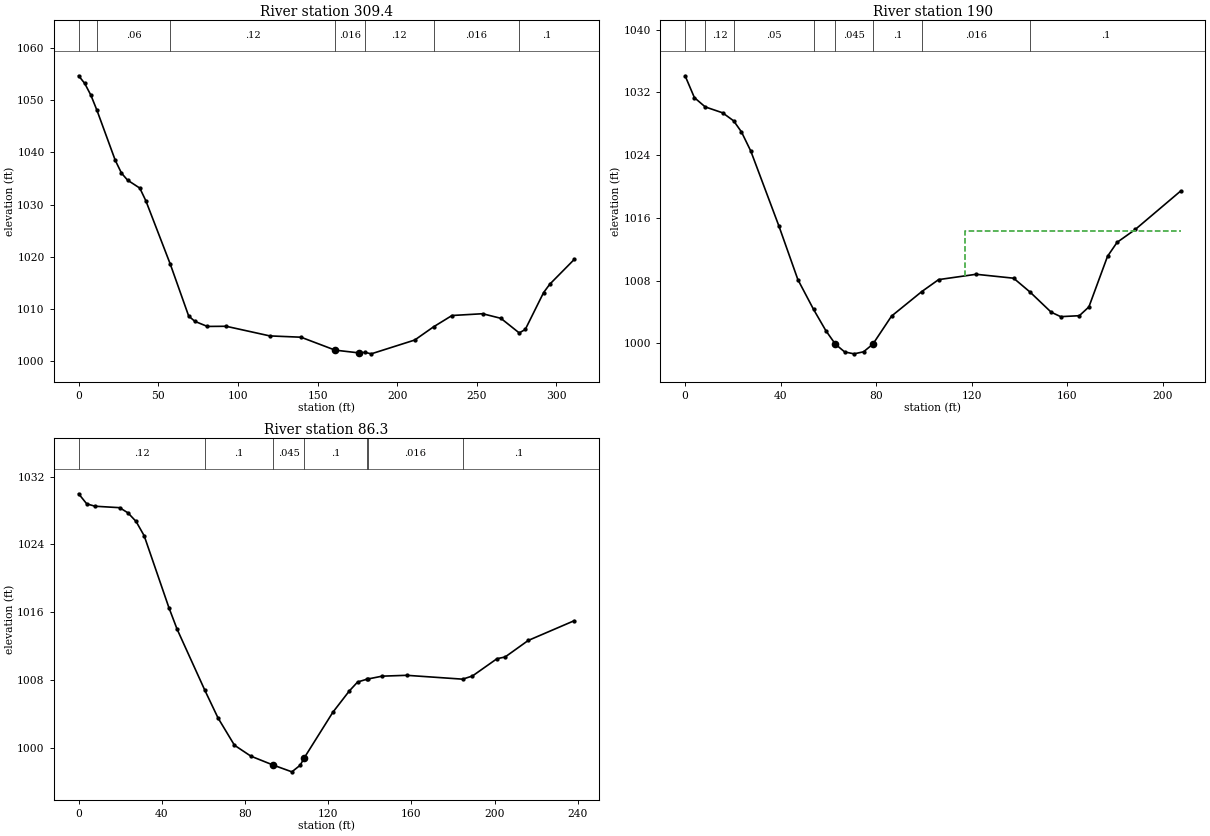
Type RM Length L Ch R = 1 ,309.4   ,148.1,119.4,76.4
XS GIS Cut Line= 6
     1764337.173      380897.071     1764383.006        380840.3
     1764455.402      380879.363     1764479.881      380880.925
     1764524.152       380896.55     1764568.423      380824.675
#Sta/Elev= 30
       0 1054.62     3.8 1053.17     7.7  1050.9    11.5 1048.02      23 1038.45
    26.9 1036.01    30.7 1034.67    38.4 1033.14    42.2 1030.72    57.6 1018.55
    69.1 1008.67      73 1007.66    80.8 1006.69    92.6 1006.72     120 1004.88
   139.6 1004.63     161 1002.16     176 1001.63   179.8 1001.73   183.7 1001.45
     211 1004.09   222.8 1006.61   234.4 1008.78   253.6 1009.12   265.1 1008.24
   276.6 1005.45   280.4 1006.11   291.9 1013.16   295.8 1014.77   311.1 1019.49
#Mann= 7 ,-1 , 0
       0      .1       0    11.5     .06       0    57.6     .12       0
     161    .016       0   179.8     .12       0   222.8    .016       0
   276.6      .1       0
Bank Sta=161,176
XS Rating Curve= 0 ,0
Exp/Cntr=0.3,0.1

Type RM Length L Ch R = 1 ,190     ,103.6,103.7,103.6
XS GIS Cut Line= 3
     1764503.845      381005.282     1764640.945      380887.478
     1764644.248      380861.049
#Sta/Elev= 30
       0 1034.11     3.9 1031.32    8.431030.141    15.7 1029.39   20.331028.364
    23.6 1026.95    27.5 1024.51    39.3 1014.93    47.2 1008.13   53.751004.342
    58.9 1001.63    62.9   999.9    66.8  998.91    70.7  998.67    74.7  998.93
    78.6  999.91    86.4 1003.48   99.071006.608   106.1 1008.13   121.8 1008.81
   137.5 1008.31  144.39 1006.54   153.2 1003.98   157.2 1003.41     165 1003.53
     169 1004.65   176.8  1011.1   180.8 1012.88   188.4 1014.52   207.4 1019.42
#Mann= 8 ,-1 , 0
       0     .06       0    8.43     .12       0   20.33     .05       0
   53.75      .1       0    62.9    .045       0    78.6      .1       0
   99.07    .016       0  144.39      .1       0
#XS Ineff= 2 , 0
                           117.3         1014.33
Permanent Ineff=
       F       F
Bank Sta=62.9,78.6
XS Rating Curve= 0 ,0
Exp/Cntr=0.3,0.1

Type RM Length L Ch R = 1 ,86.3    ,77.6,86.3,94.9
XS GIS Cut Line= 3
     1764561.824      381090.546     1764717.333      380956.923
     1764721.453       380923.97
#Sta/Elev= 30
       0 1029.98     3.9 1028.79     7.9 1028.51    19.7 1028.34    23.7 1027.73
    27.6 1026.72    31.5 1025.03    43.4 1016.54    47.3 1014.02   60.711006.773
      67 1003.53    74.9 1000.31    82.8  999.02    93.5  997.97   102.5  997.17
   106.5  997.95   108.5  998.84   122.2  1004.2   130.1 1006.71   134.1 1007.77
  138.591008.101  139.261008.136   145.9 1008.46   157.7 1008.56  184.581008.105
   189.3 1008.48   201.1 1010.52     205 1010.72   216.1 1012.67   238.2    1015
#Mann= 7 ,-1 , 0
       0     .12       0   60.71      .1       0    93.5    .045       0
   108.5      .1       0  138.59     .05       0  139.26    .016       0
  184.58      .1       0
Bank Sta=93.5,108.5
XS Rating Curve= 0 ,0
Exp/Cntr=0.3,0.1

Chan Stop Cuts=-1
Use User Specified Reach Order=0
Composite Channel Slope=5